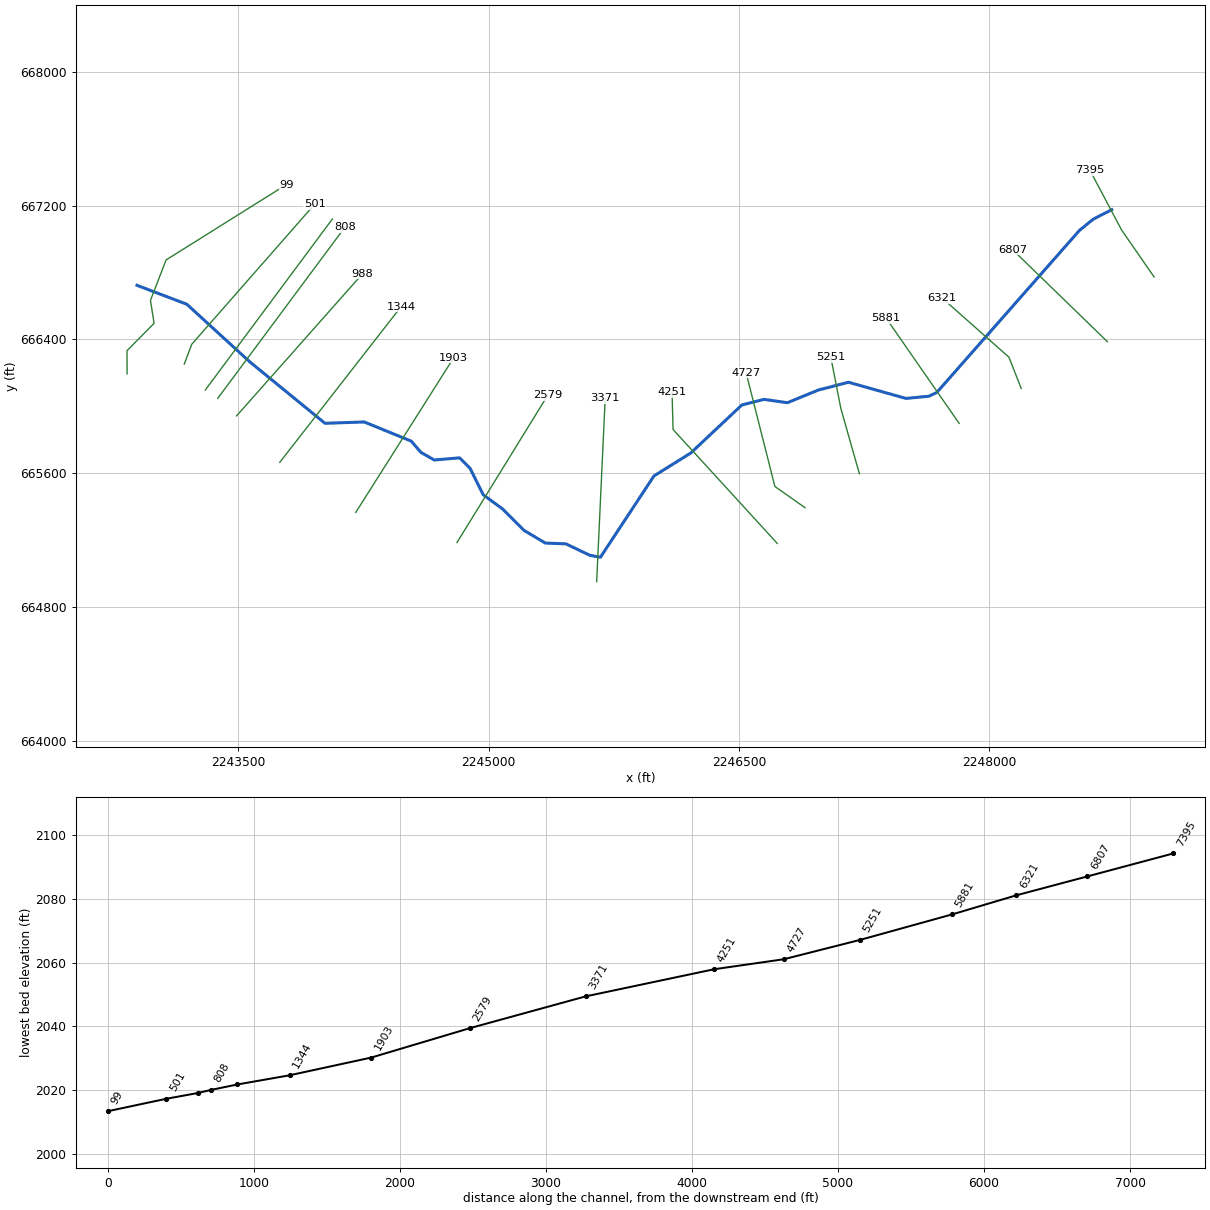
--- CASSITYFK_DS.prj (project) ---

Proj Title=CASSITYFK_DS
Current Plan=p01
Default Exp/Contr=0,0
English Units
Geom File=g01
Flow File=f01
Plan File=p01
BEGIN DESCRIPTION:
----------MODEL BY WOOD PLC 2022----------
AFH study
Randolph County, WV
HEC-RAS Version: RAS 6.2
Vertical Datum: NAVD88
Projection: NAD 1983 StatePlane West Virginia S FIPS 4702 (US Feet)
Terrain: 1-meter LIDAR (FEMA Region III 3DEP collected 2016-2018)
Land Use: 2019 NLCD
Hydrologic Method:
WV SIR2010-5033 regression equations
Additional Model Notes:
Model was originally CASSITYFK; this is the lower reach from the confluence with PANTHRN. Shared XS used for PANTHRN and CASSITYFK_US
END DESCRIPTION:
DSS Export Rating Curves= 0
DSS Export Rating Curve Sorted= 0
DSS Export Volume Flow Curves= 0
DXF OffsetX= 0
DXF OffsetY= 0
DXF ScaleX= 0
DXF ScaleY= 0

--- CASSITYFK_DS.p01 (plan) ---

Plan Title=Floodplain
Program Version=6.20
Short Identifier=Floodplain
Geom File=g01
Flow File=f01
Subcritical Flow
K Sum by GR= 0
Std Step Tol= 0.01
Critical Tol= 0.01
Num of Std Step Trials= 20
Max Error Tol= 0.3
Flow Tol Ratio= 0.001
Split Flow NTrial= 30
Split Flow Tol= 0.02
Split Flow Ratio= 0.02
Log Output Level= 0
Friction Slope Method= 1
Unsteady Friction Slope Method= 2
Unsteady Bridges Friction Slope Method= 1
Parabolic Critical Depth
Global Vel Dist= 0 , 0 , 0
Global Log Level= 0
CheckData=True
Encroach Param=-1 ,0,0, 0
Mapping Interval=1HOUR
Computation Time Step Use Courant=        0
Computation Time Step Use Time Series=    0
Computation Time Step Count To Double=0
Computation Time Step Max Doubling=0
Computation Time Step Max Halving=0
Computation Time Step Residence Courant=0
Run HTab= 0
Run UNet= 0
Run Sediment= 0
Run PostProcess= 0
Run WQNet= 0
Run RASMapper=-1
UNET Theta= 0
UNET Theta Warmup= 0
UNET ZTol= 0
UNET ZSATol= 0
UNET MxIter= 0
UNET Max Iter WO Improvement= 0
UNET MaxInSteps= 0
UNET DtIC= 0
UNET DtMin= 0
UNET MaxCRTS= 0
UNET WFStab= 0
UNET SFStab= 0
UNET WFX= 1
UNET SFX= 1
UNET Gravity=32.174
UNET 1D Methodology=Finite Difference
UNET DSS MLevel= 1
UNET Pardiso=0
UNET DZMax Abort= 0
UNET Use Existing IB Tables= 0
UNET Froude Reduction=False
UNET Froude Limit= 0
UNET Froude Power= 0
UNET D1 Cores= 0
UNET WindReference=Eulerian
UNET WindDragFormulation=Hsu (1988)
UNET D2 Coriolis=0
UNET D2 Cores= 0
UNET D2 Theta= 1
UNET D2 Theta Warmup= 1
UNET D2 Z Tol= 0.01
UNET D2 Volume Tol= 0.01
UNET D2 Max Iterations= 20
UNET D2 Equation= 0
UNET D2 RampUpFraction=0.1
UNET D2 TimeSlices= 1
UNET D2 Turbulence Formulation=Non-Conservative (original)
UNET D2 Eddy Viscosity=0.3
UNET D2 Transverse Eddy Viscosity=0.1
UNET D2 Smagorinsky Mixing=0
UNET D2 BCVolumeCheck=0
UNET D2 Cores=0
UNET D2 SolverType=PARDISO (Direct)
UNET D2 Minimum Iterations= 2147483647
UNET D2 Maximum Iterations= 2147483647
UNET D2 Restart Number= 10
UNET D2 Relaxation Coeff=1.3
UNET D2 SOR Precondition Iterations= 10
UNET D2 ILUT Maximum Fill= 8
UNET D2 ILUT Tolerance=1E-08
UNET D1D2 MaxIter= 0
UNET D1D2 ZTol=0.01
UNET D1D2 QTol=0.1
UNET D1D2 MinQTol=1
Write IC File= 0
Write IC File at Fixed DateTime=0
Write IC File at Sim End=0
Echo Input=False
Echo Parameters=False
Echo Output=False
Write Detailed= 0
HDF Write Warmup=0
HDF Write Time Slices=0
HDF Flush=0
HDF Compression= 1
HDF Chunk Size= 1
HDF Spatial Parts= 1
HDF Use Max Rows=0
HDF Fixed Rows= 1
Calibration Method= 0
Calibration Iterations= 20
Calibration Max Change=0.05
Calibration Tolerance=0.2
Calibration Maximum=1.5
Calibration Minimum=0.5
Calibration Optimization Method= 1
WQ AD Non Conservative
WQ ULTIMATE=-1
WQ Max Comp Step=1HOUR
WQ Output Interval=15MIN
WQ Output Selected Increments= 0
WQ Output face flow=0
WQ Output face velocity=0
WQ Output face area=0
WQ Output face dispersion=0
WQ Output cell volume=0
WQ Output cell surface area=0
WQ Output cell continuity=0
WQ Output cumulative cell continuity=0
WQ Output face conc=0
WQ Output face dconc_dx=0
WQ Output face courant=0
WQ Output face peclet=0
WQ Output face adv mass=0
WQ Output face disp mass=0
WQ Output cell mass=0
WQ Output cell source sink temp=0
WQ Output nsm pathways=0
WQ Output nsm derived pathways=0
WQ Create Restart=0
WQ Fixed Restart=0
WQ System Summary=0
WQ Write To DSS=0
Sorting and Armoring Iterations= 10
XS Update Threshold= 0.02
Bed Roughness Predictor= 0
Hydraulics Update Threshold= 0.02
Energy Slope Method= 1
Volume Change Method= 1
Sediment Retention Method= 0
Sediment TS Multiplier= 1
Warm Up Method= 0
XS Weighting Method= 0
Number of US Weighted Cross Sections= 1
Number of DS Weighted Cross Sections= 1
Upstream XS Weight=0
Main XS Weight=1
Downstream XS Weight=0
Number of DS XS's Weighted with US Boundary= 1
Upstream Boundary Weight= 1
Weight of XSs Associated with US Boundary= 0
Number of US XS's Weighted with DS Boundary= 1
Downstream Boundary Weight= 0.5
Weight of XSs Associated with DS Boundary= 0.5
Percentile Method= 0
Sediment Output Level= 3
Mass or Volume Output= 0
Output Increment Type= 1
Profile and TS Output Increment= 1
Transport Output Increment 1
XS Output Flag= 0
XS Output Increment= 10
Read HDF5 Sediment Hotstart= 0
Sediment Hotstart Type= 0
Write Gradation File= 0
Read Gradation Hotstart= 0
Write HDF5 File= 1
Write Binary Output= 1
Write DSS Sediment File= 0
DSS Sediment Output Type= 1
SV Curve= 0
Specific Gage Flag= 0
Subcell Erosion Methods= 0
Subcell Deposition Methods= 0
Advection Scheme= 1
Matrix Solver= 0
Implicit Weighting Factor= 1
Maximum Outer Loop Convergence Iterations= 5
Convergence Maximum Absolute= 0.001
Convergence RMSE= 0.0001
Grain Fractions Max Abs Error= 0.001
Max Subgrid Regions= 1
Max Subgrid Length Scale= 3.402823E+38
Initial Layer Thickness= 3.402823E+38
Min Layer Thickness= 3.402823E+38
Max Layer Thickness= 3.402823E+38
Number of Layers= 5

--- CASSITYFK_DS.f01 (steady flow) ---

Flow Title=Flow
Program Version=6.20
Number of Profiles= 1
Profile Names=P100yr
River Rch & RM=CASSITYFK_DS,Main,7395
    2720
Boundary for River Rch & Prof#=CASSITYFK_DS,Main            , 1
Up Type= 0
Dn Type= 3
Dn Slope=0.013047
DSS Import GetInterval= 0
DSS Import GetPeak= 0
DSS Import FillOption= 0

--- CASSITYFK_DS.g01 (geometry) ---

Geom Title=Geometry
Program Version=6.20

River Reach=CASSITYFK_DS    ,Main
Reach XY= 30
2248733.89995812667175.738041882     2248622.973      667118.988
     2248539.786       667051.262247685.68489557666082.700083953
      2247638.35      666060.2842247500.99917357666046.976586787
     2247157.158      666143.5922246978.07813774 666098.05482038
2246790.36672453 666021.39091019      2246650.13      666041.413
     2246517.447      666007.678     2246211.407      665720.474
     2245990.921      665583.322     2245670.337      665097.431
      2245607.24      665108.6692245463.88713774665177.162676597
2245340.18750302 665182.213269432245211.94003404 665258.11846344
2245084.59374603665385.4647514442244967.61955388665471.322656026
     2244889.728       665628.38     2244826.439      665691.673
2244674.89595974665678.7645731362244594.92482038665724.113544905
     2244536.995       665791.54     2244255.374       665906.26
2244019.87340717665898.341808289     2243567.809       666267.05
2243192.59664808666609.954900656     2242893.431      666723.456

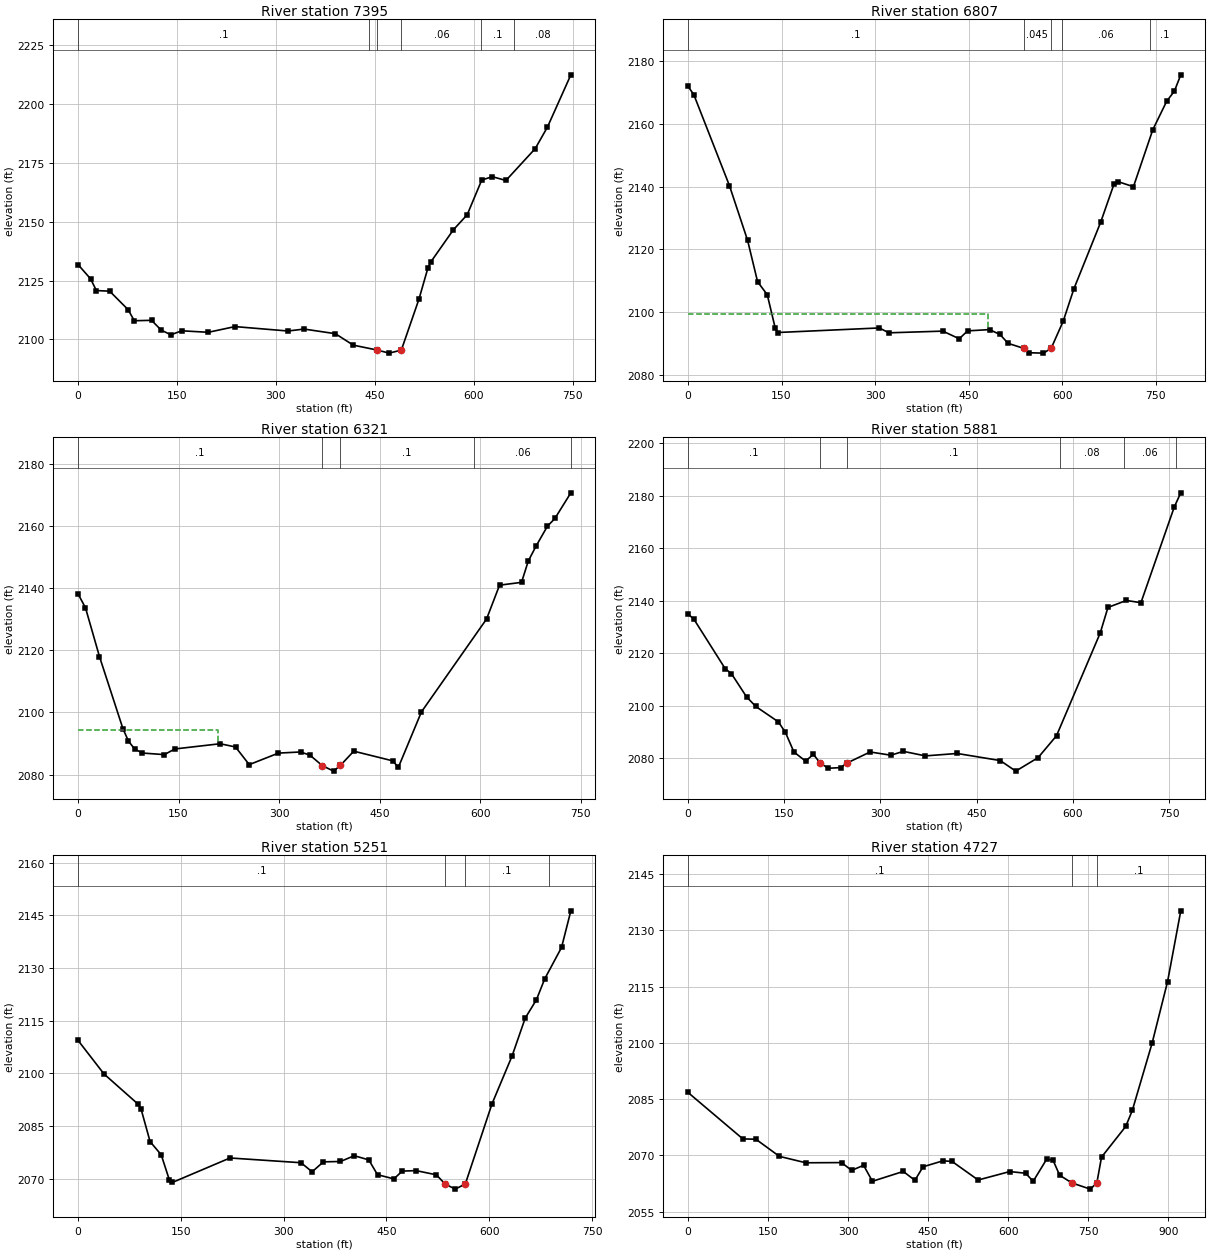
Type RM Length L Ch R = 1 ,7395    ,581.5,588.7,593
XS GIS Cut Line= 3
2248987.35181014666773.654393358 2248792.8001628667054.220399501
  2248602.439804667412.481775581
#Sta/Elev= 30
       0 2131.75    18.9 2125.73    27.8 2120.73    47.9 2120.48    75.8 2112.67
    85.3 2107.94   111.4 2108.12     126 2103.99   140.6 2101.98   157.2 2103.68
   197.4 2103.04   237.9 2105.46   318.1 2103.59   342.8 2104.41   390.1 2102.45
   417.2  2097.6  453.912095.489   471.6 2094.21  490.11 2095.49   516.9 2117.16
   530.4 2130.31     535 2132.95   568.9 2146.46     590 2152.91     612 2167.59
     628 2169.01   648.7 2167.42   693.1 2180.92   711.7 2190.09   747.1  2212.2
#Mann= 6 ,-1,0
       0      .1       0  441.42     .06       0  453.91    .045       0
  490.11     .06       0  611.42      .1       0  661.42     .08       0
Bank Sta=453.91,490.11
XS Rating Curve= 0 ,0
Exp/Cntr=0.3,0.1

Type RM Length L Ch R = 1 ,6807    ,484.8,485.8,487
XS GIS Cut Line= 2
2248707.47405907666386.6377017342248139.92462533666936.298425801
#Sta/Elev= 30
       0 2171.91     9.4 2169.21    66.4 2140.33    95.6 2122.87   111.6 2109.71
   127.1  2105.6   139.9 2094.96   143.8 2093.57   306.8 2095.02     322 2093.47
   408.6 2094.01   434.9 2091.58   448.3 2094.09   483.5 2094.49   500.2 2092.94
   513.3 2090.12  538.222088.527   547.3 2087.13   569.9 2087.01  582.272088.527
   601.6 2097.18   618.9 2107.56   661.7 2128.67     683 2140.76   689.5 2141.56
   714.2 2139.95   745.2 2158.05   767.5 2167.13   779.9 2170.37   790.1 2175.54
#Mann= 5 ,-1,0
       0      .1       0  538.22    .045       0  582.27      .1       0
     600     .06       0     740      .1       0
#XS Ineff= 2 , 0
          481.65 2099.55
Permanent Ineff=
       F       F
Bank Sta=538.22,582.27
XS Rating Curve= 0 ,0
Exp/Cntr=0.3,0.1

Type RM Length L Ch R = 1 ,6321    ,445.6,440.2,435.9
XS GIS Cut Line= 3
2248191.32956532666106.8232405992248117.79148892666293.737532401
2247717.03872812666647.564875333
#Sta/Elev= 30
       0 2138.09    11.1 2133.62      32 2117.91      67 2094.73    75.2 2090.76
    84.5 2088.18      96 2086.91   128.8  2086.4   144.4 2088.22   212.1  2089.9
     235 2088.86   255.5 2083.18   299.1 2086.89     332 2087.25   346.1 2086.23
  364.522082.859   381.3 2081.09   391.5 2082.92   411.5 2087.51   469.8 2084.39
     478 2082.28   512.5 2100.14   609.7 2130.02   629.1 2140.91   661.9 2141.81
     672  2148.7   683.5 2153.44   700.4 2159.83   711.7 2162.36   735.5 2170.61
#Mann= 5 ,-1,0
       0      .1       0  364.52    .045       0   391.5      .1       0
  590.86     .06       0  735.46      .1       0
#XS Ineff= 2 , 0
          209.05 2094.24
Permanent Ineff=
       F       F
Bank Sta=364.52,391.5
XS Rating Curve= 0 ,0
Exp/Cntr=0.3,0.1

Type RM Length L Ch R = 1 ,5881    ,640.6,630.2,619.8
XS GIS Cut Line= 2
2247819.77294593665897.6225756692247381.14900793666528.221141934
#Sta/Elev= 30
       0 2135.01     9.2 2133.02    57.9 2114.19    67.7 2112.26    91.3 2103.41
   105.7 2099.75   140.8  2093.9   151.7 2089.94   165.1 2082.41   183.3  2078.9
   195.4 2081.51   206.3 2078.13   218.7 2076.19   238.2 2076.45  247.142078.102
   283.9  2082.4   316.2 2081.17   335.7 2082.63   370.1 2080.91   419.6 2081.83
   486.7 2079.13   510.9  2075.1   545.7 2080.24   574.4 2088.59   642.6  2127.8
   654.6 2137.51   683.3 2140.16     706 2139.31     758 2175.82   768.1 2181.19
#Mann= 6 ,-1,0
       0      .1       0   206.3    .045       0  247.14      .1       0
     580     .08       0     680     .06       0     760      .1       0
Bank Sta=206.3,247.14
XS Rating Curve= 0 ,0
Exp/Cntr=0.3,0.1

Type RM Length L Ch R = 1 ,5251    ,520.6,523.1,523.3
XS GIS Cut Line= 3
2247221.75305634665596.8688465772247110.51458837665987.836188298
2247050.48613015666294.582739708
#Sta/Elev= 30
       0 2109.41    37.8 2099.88    87.7 2091.26    91.8 2089.98   105.1 2080.62
   121.3 2076.89   133.4 2069.61   137.5    2069   221.7 2075.97   325.3 2074.62
   341.5 2072.04     358 2074.87   382.9 2074.97     403 2076.61   424.2 2075.43
   436.9 2071.21   460.8 2070.03   473.1 2072.24   493.4 2072.37   522.8 2071.18
   535.7 2068.53   550.5 2067.11  565.082068.604   603.9 2091.34   633.3 2105.01
   652.4 2115.75   668.7 2120.94   680.9 2126.93   705.4 2135.84     719 2146.27
#Mann= 4 ,-1,0
       0      .1       0   535.7    .045       0  565.08      .1       0
  686.48     .06       0
Bank Sta=535.7,565.08
XS Rating Curve= 0 ,0
Exp/Cntr=0.3,0.1

Type RM Length L Ch R = 1 ,4727    ,461.7,476.3,485
XS GIS Cut Line= 3
2246896.31263308665393.5000077062246715.53913015665520.342842527
2246542.84399807666201.150603782
#Sta/Elev= 30
       0  2086.8   102.8 2074.42   127.2 2074.34   171.2 2069.77   220.8 2068.06
   287.7 2068.11   306.6 2066.03     329 2067.39   345.5 2063.13   403.3 2065.75
   425.1 2063.39   440.4 2066.99   477.8 2068.59   494.8 2068.41   543.6 2063.47
   602.8 2065.72   632.5 2065.27   646.7 2063.13     672 2069.03   683.9 2068.74
   696.3 2064.74  719.112062.696   753.7 2061.04  765.982062.698   774.7 2069.56
   820.1 2077.75   832.4 2082.01   869.5 2099.94   898.5 2116.36   923.2 2135.19
#Mann= 3 ,-1,0
       0      .1       0  719.11    .045       0  765.98      .1       0
Bank Sta=719.11,765.98
XS Rating Curve= 0 ,0
Exp/Cntr=0.3,0.1

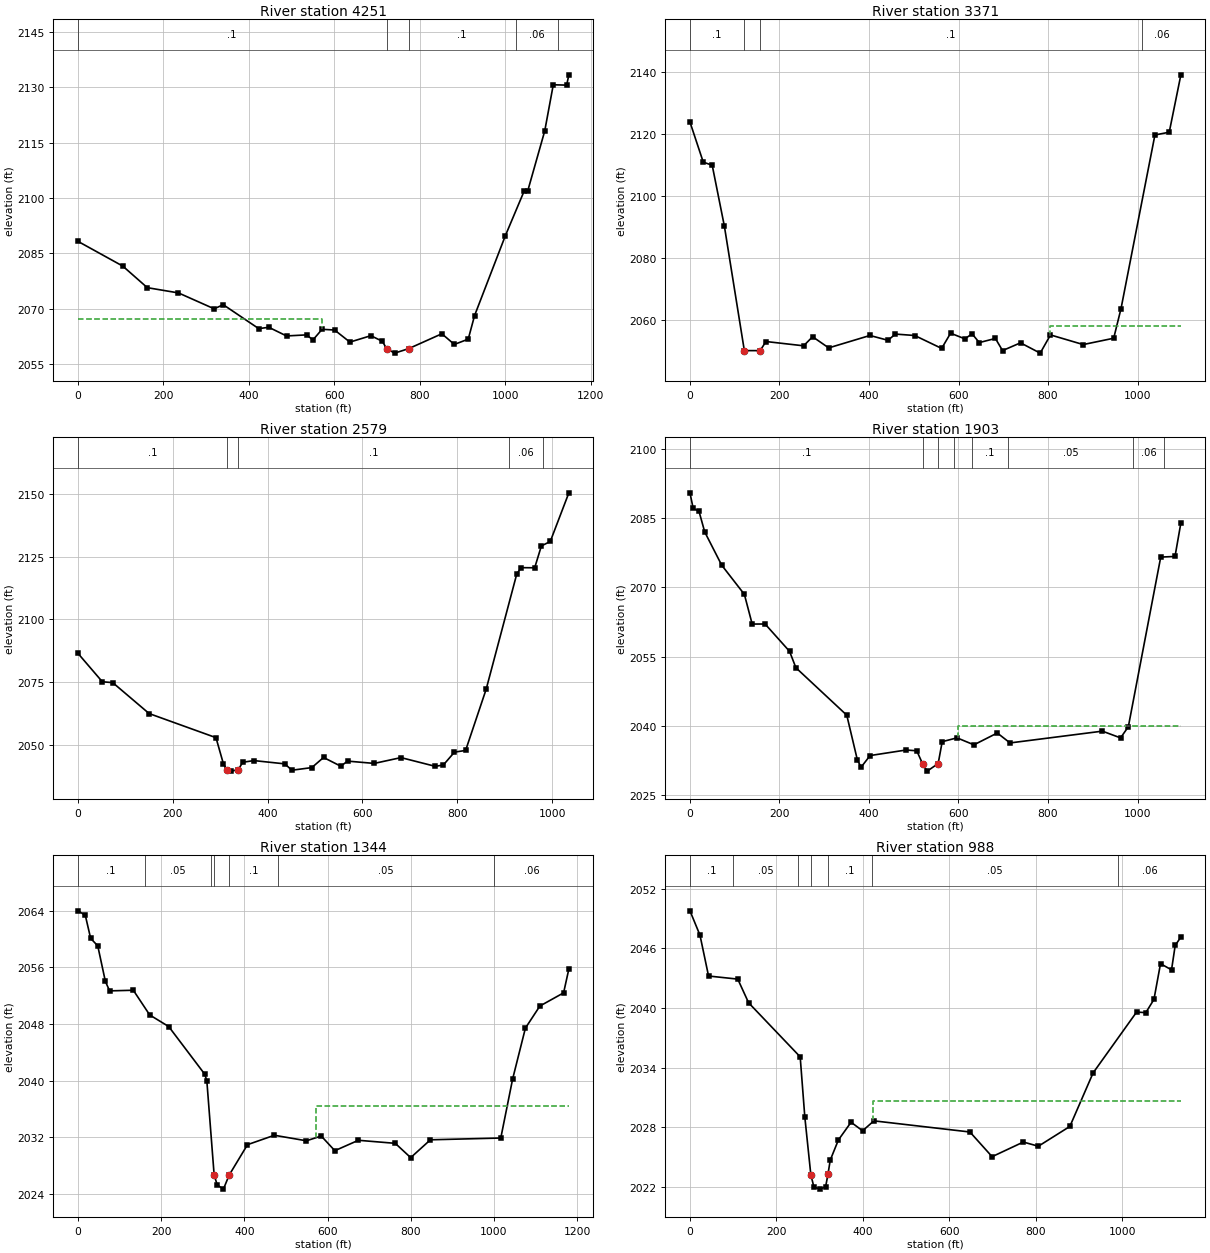
Type RM Length L Ch R = 1 ,4251    ,896.6,880.1,872.3
XS GIS Cut Line= 3
2246729.82384108665179.8278742412246105.50659812665861.272185176
2246099.38584084 666085.69995225
#Sta/Elev= 30
       0 2088.22   104.9 2081.51   162.3 2075.66   235.1 2074.24   318.7 2069.93
     340 2071.04   422.9 2064.56   446.7 2064.91     488 2062.57   535.4 2062.86
   549.7 2061.47   571.2 2064.37   600.5 2064.18   636.3  2060.9   685.4 2062.64
   712.5  2061.1     7222059.127     741 2057.91  773.752059.122   851.5 2063.16
   880.7 2060.27   913.2  2061.7   928.1 2068.11  1000.1 2089.76  1044.1 2101.87
  1052.2  2101.8  1092.2 2118.15  1112.2 2130.68  1143.5 2130.59  1148.7 2133.38
#Mann= 5 ,-1,0
       0      .1       0     722    .045       0  773.75      .1       0
  1024.2     .06       0  1124.2      .1       0
#XS Ineff= 2 , 0
          570.93 2067.27
Permanent Ineff=
       F       F
Bank Sta=722,773.75
XS Rating Curve= 0 ,0
Exp/Cntr(USF)=0,0
Exp/Cntr=0.3,0.1

Type RM Length L Ch R = 1 ,3371    ,801.7,791.9,784.7
XS GIS Cut Line= 2
2245647.74719822 664951.524241342245698.75350892666047.139795148
#Sta/Elev= 30
       0 2123.89    29.7 2110.97    49.7 2109.96    76.9 2090.32   121.5 2050.21
  156.81 2050.21   169.8 2053.14   253.9 2051.76     274 2054.68     310 2051.09
   402.1 2055.09   442.3 2053.54   459.1 2055.54   502.2 2055.08   562.3 2050.92
   582.3 2055.82   614.3    2054   630.3 2055.63   646.4  2052.8   682.4 2054.13
   698.4 2050.22   738.5 2052.72   782.5  2049.4   805.5 2055.27   878.6 2052.16
   946.7  2054.2   963.1 2063.77  1038.8 2119.72  1070.8 2120.61  1096.8 2139.11
#Mann= 4 ,-1,0
       0      .1       0   121.5    .045       0  156.81      .1       0
    1010     .06       0
#XS Ineff= 2 , 0
                           803.9          2058.2
Permanent Ineff=
       F       F
Bank Sta=121.5,156.81
XS Rating Curve= 0 ,0
Exp/Cntr(USF)=0,0
Exp/Cntr=0.3,0.1

Type RM Length L Ch R = 1 ,2579    ,674.3,676,669.1
XS GIS Cut Line= 2
2244810.94955272665185.4778292542245354.87943498666066.481992041
#Sta/Elev= 30
       0 2086.46    51.4 2075.12    73.3 2074.78   150.1 2062.43   291.1 2052.81
   306.9 2042.28   314.2 2040.04   323.3 2039.45   338.1 2040.04   347.5 2042.98
     371 2043.66   436.3 2042.35   451.2 2039.81   493.2 2040.86     518  2044.9
   554.4 2041.41   568.5 2043.45   624.9 2042.53   681.3 2044.85   753.5 2041.37
   770.6 2041.89   794.1 2047.03   817.6 2047.71     861 2072.16   925.7 2118.28
   935.1 2120.67   963.3 2120.62   977.4 2129.34   996.2 2131.13  1035.4 2150.54
#Mann= 5 ,-1,0
       0      .1       0   314.2    .045       0   338.1      .1       0
     910     .06       0     980      .1       0
Bank Sta=314.2,338.1
XS Rating Curve= 0 ,0
Exp/Cntr(USF)=0,0
Exp/Cntr=0.3,0.1

Type RM Length L Ch R = 1 ,1903    ,564,559,558.5
XS GIS Cut Line= 2
2244204.29335271 665365.279773592244791.88605196666291.554375879
#Sta/Elev= 30
       0 2090.43     7.2 2087.05    20.1 2086.46      33 2081.96    70.9 2074.78
   121.6 2068.46     139 2062.04   167.9 2062.05   222.5 2056.14   236.7 2052.59
   350.4 2042.32   374.1 2032.62   382.4 2031.07   402.5 2033.59     483 2034.79
   506.7 2034.62  519.992031.774   530.2 2030.22  554.632031.868   563.6 2036.59
   596.7 2037.42   634.5 2035.91   686.7 2038.47   715.2 2036.32   921.5 2038.87
   962.1 2037.41   979.5 2039.82  1051.9 2076.53  1083.8 2076.66  1096.9 2083.91
#Mann= 8 ,-1,0
       0      .1       0  519.99    .045       0  554.63      .1       0
     590     .05       0     630      .1       0     710     .05       0
     990     .06       0    1060      .1       0
#XS Ineff= 2 , 0
                          598.57         2039.97
Permanent Ineff=
       F       F
Bank Sta=519.99,554.63
XS Rating Curve= 0 ,0
Exp/Cntr(USF)=0,0
Exp/Cntr=0.3,0.1

Type RM Length L Ch R = 1 ,1344    ,357.7,356.5,355.4
XS GIS Cut Line= 2
2243749.31706128665665.1968804992244475.64692563666595.551987643
#Sta/Elev= 30
       0 2063.99    17.6 2063.37    30.5  2060.1    47.6 2059.04    65.9 2054.02
    76.1 2052.68   133.1 2052.77   172.5 2049.28   218.2 2047.64   304.5 2040.93
   309.8 2040.01  327.42 2026.67   334.9 2025.25   349.7 2024.67   363.7 2026.67
   407.6 2030.95   472.2 2032.28   549.2  2031.5     585 2032.17   617.6  2030.1
   674.2 2031.57   762.9 2031.14     800 2029.12   847.4 2031.64  1016.6 2031.89
    1045 2040.21  1075.8 2047.42  1110.6 2050.54  1167.6  2052.4  1180.3 2055.78
#Mann= 7 ,-1,0
       0      .1       0     160     .05       0     320      .1       0
  327.42    .045       0   363.7      .1       0     480     .05       0
    1000     .06       0
#XS Ineff= 2 , 0
                          572.84         2036.36
Permanent Ineff=
       F       F
Bank Sta=327.42,363.7
XS Rating Curve= 0 ,0
Exp/Cntr(USF)=0,0
Exp/Cntr=0.3,0.1

Type RM Length L Ch R = 1 ,988     ,177.3,179.1,181
XS GIS Cut Line= 2
 2243490.1090355665942.5054464872244244.19245363666791.778881892
#Sta/Elev= 30
       0 2049.76    23.2 2047.31      43 2043.21   110.6  2042.9   135.7 2040.52
     255 2035.09   265.7 2029.05  279.572023.269   286.7 2022.01   300.9  2021.8
   313.8 2022.04  319.222023.271   324.5 2024.71   343.4 2026.74   372.7 2028.52
   399.4 2027.66   425.5 2028.66   647.7 2027.54     699 2025.06   771.2 2026.53
     806 2026.11   878.9  2028.1   932.7 2033.48  1033.3 2039.59  1054.6 2039.53
  1073.4 2040.86  1088.6 2044.45  1114.1 2043.83  1122.6 2046.29  1135.7 2047.12
#Mann= 7 ,-1,0
       0      .1       0     100     .05       0     250      .1       0
  279.57    .045       0  319.22      .1       0     420     .05       0
     990     .06       0
#XS Ineff= 2 , 0
                          424.15         2030.64
Permanent Ineff=
       F       F
Bank Sta=279.57,319.22
XS Rating Curve= 0 ,0
Exp/Cntr(USF)=0,0
Exp/Cntr=0.3,0.1

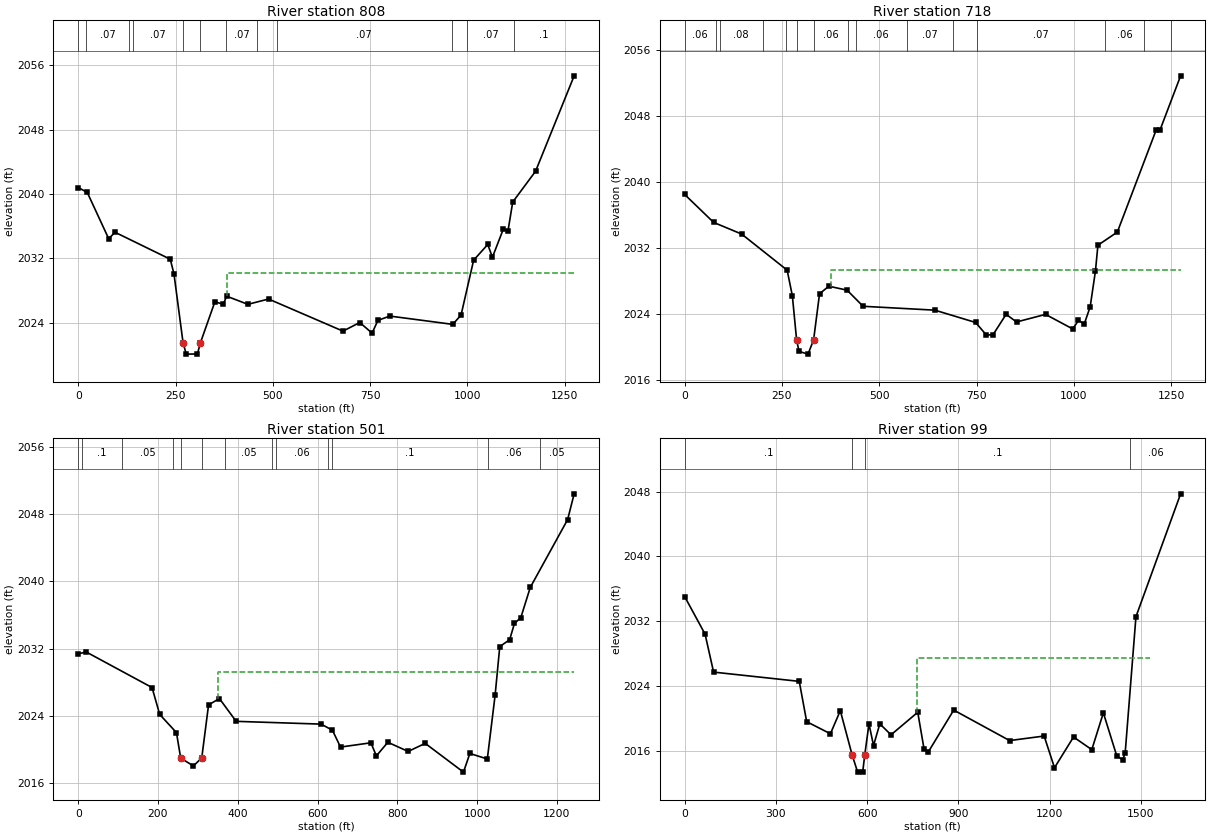
Type RM Length L Ch R = 1 ,808     ,90.7,90,90.5
XS GIS Cut Line= 2
2243377.42506332666047.5143305882244138.43921894667069.680796989
#Sta/Elev= 30
       0 2040.82    23.2 2040.22    78.3 2034.46    94.6 2035.26   236.5 2031.91
   246.1 2030.07  269.352021.536   277.6 2020.11   306.3 2020.13  314.122021.537
   351.2 2026.62     373  2026.3   381.1 2027.32   435.9  2026.3   489.1 2026.96
   680.3 2022.97   723.5 2024.04   755.1 2022.72   770.1 2024.31   800.7 2024.84
   962.4 2023.81   983.7 2024.97    1016 2031.79  1052.3 2033.74  1064.3 2032.15
  1092.3 2035.66  1104.2  2035.4  1116.5 2039.02  1175.2 2042.85  1274.3 2054.71
#Mann= 12 ,-1,0
       0      .1       0      20     .07       0     130     .05       0
     140     .07       0  269.35    .045       0  314.12     .05       0
     380     .07       0     460     .06       0     510     .07       0
     960     .05       0    1000     .07       0    1120      .1       0
#XS Ineff= 2 , 0
                          381.41         2030.23
Permanent Ineff=
       F       F
Bank Sta=269.35,314.12
XS Rating Curve= 0 ,0
Exp/Cntr(USF)=0,0
Exp/Cntr=0.3,0.1

Type RM Length L Ch R = 1 ,718     ,218.4,217.2,214.8
XS GIS Cut Line= 2
 2243302.9558497666097.5005150732244063.97000532667119.666981474
#Sta/Elev= 30
       0 2038.46    74.4 2035.08   146.4 2033.67   263.3  2029.3   276.7 2026.19
  287.582020.861   293.8 2019.47   316.9 2019.14  331.262020.861   346.5 2026.44
   370.4 2027.36   417.3 2026.88   458.4 2024.93   642.9 2024.46   747.6 2022.97
   775.3 2021.44   792.5  2021.5   825.9 2023.96   852.7 2023.03   927.2 2023.95
     997 2022.19  1011.9 2023.21  1026.9 2022.81  1041.9 2024.87  1055.5 2029.22
  1061.8 2032.32  1111.7 2033.91  1211.4 2046.26  1221.4 2046.27  1274.3 2052.82
#Mann= 15 ,-1,0
       0     .06       0      80     .07       0      90     .08       0
     200     .06       0     260     .07       0  287.58    .045       0
  331.26     .06       0     420     .07       0     440     .06       0
     570     .07       0     690     .06       0     750     .07       0
    1080     .06       0    1180     .05       0    1250      .1       0
#XS Ineff= 2 , 0
                          376.97          2029.3
Permanent Ineff=
       F       F
Bank Sta=287.58,331.26
XS Rating Curve= 0 ,0
Exp/Cntr(USF)=0,0
Exp/Cntr=0.3,0.1

Type RM Length L Ch R = 1 ,501     ,388.8,402.3,411.8
XS GIS Cut Line= 3
2243176.93190929666252.3502428972243221.72685096666370.997951613
2243958.95310843667209.556079524
#Sta/Elev= 30
       0  2031.4    20.5  2031.6   185.1 2027.38   204.3 2024.18   246.3 2022.02
  256.992018.979   288.8 2018.06  309.732019.007   326.8 2025.32     354 2026.07
     396 2023.36   609.1 2023.03   637.4  2022.3   657.6  2020.3   733.8 2020.81
   747.5 2019.25   776.3 2020.87   827.2 2019.78     870 2020.74   965.9 2017.32
   981.9 2019.54  1025.7 2018.88  1045.3  2026.5  1056.9 2032.25  1081.7 2033.07
  1093.7    2035  1109.7  2035.7  1133.4 2039.29    1227 2047.35  1243.4 2050.42
#Mann= 13 ,-1,0
       0     .05       0      10      .1       0     110     .05       0
  236.82      .1       0  256.99    .045       0  309.73      .1       0
  366.82     .05       0  486.82     .07       0  496.82     .06       0
  626.82     .05       0  636.82      .1       0 1026.82     .06       0
 1156.82     .05       0
#XS Ineff= 1 ,-1
  350.281243.371 2029.24
Permanent Ineff=
       F
Bank Sta=256.99,309.73
XS Rating Curve= 0 ,0
Exp/Cntr(USF)=0,0
Exp/Cntr=0.3,0.1

Type RM Length L Ch R = 1 ,99      ,,,
BEGIN DESCRIPTION:
orientation is necessary for visual tie in
END DESCRIPTION:
XS GIS Cut Line= 6
2242834.06619791666194.0981274442242833.81622018 666332.74035205
2242996.12490704666496.2513673352242974.31664709 666633.00569922
  2243067.770118666875.1373456762243788.35898414667325.448551647
#Sta/Elev= 30
       0 2035.05    67.1 2030.42    95.1 2025.74   376.8  2024.6   401.2 2019.63
   479.3 2018.14   511.8 2020.99  550.342015.576   568.8 2013.41   585.6 2013.47
  592.112015.495   606.1 2019.37     621 2016.69   641.8 2019.36   678.6 2018.01
   766.5 2020.79   787.4 2016.22   801.6 2015.92   884.8 2021.06  1068.7  2017.3
  1182.2 2017.86  1216.2 2013.95  1278.8 2017.74  1338.9 2016.18  1376.9 2020.72
  1421.3 2015.37  1440.9 2014.95  1448.7 2015.79  1484.1 2032.57    1631 2047.72
#Mann= 4 ,-1,0
       0      .1       0  550.34    .045       0  592.11      .1       0
 1464.96     .06       0
#XS Ineff= 1 ,-1
   762.9  1531.82027.503
Permanent Ineff=
       F
Bank Sta=550.34,592.11
XS Rating Curve= 0 ,0
Exp/Cntr(USF)=0,0
Exp/Cntr=0.3,0.1
LCMann Table=0

Chan Stop Cuts=-1
Use User Specified Reach Order=0
Composite Channel Slope=5